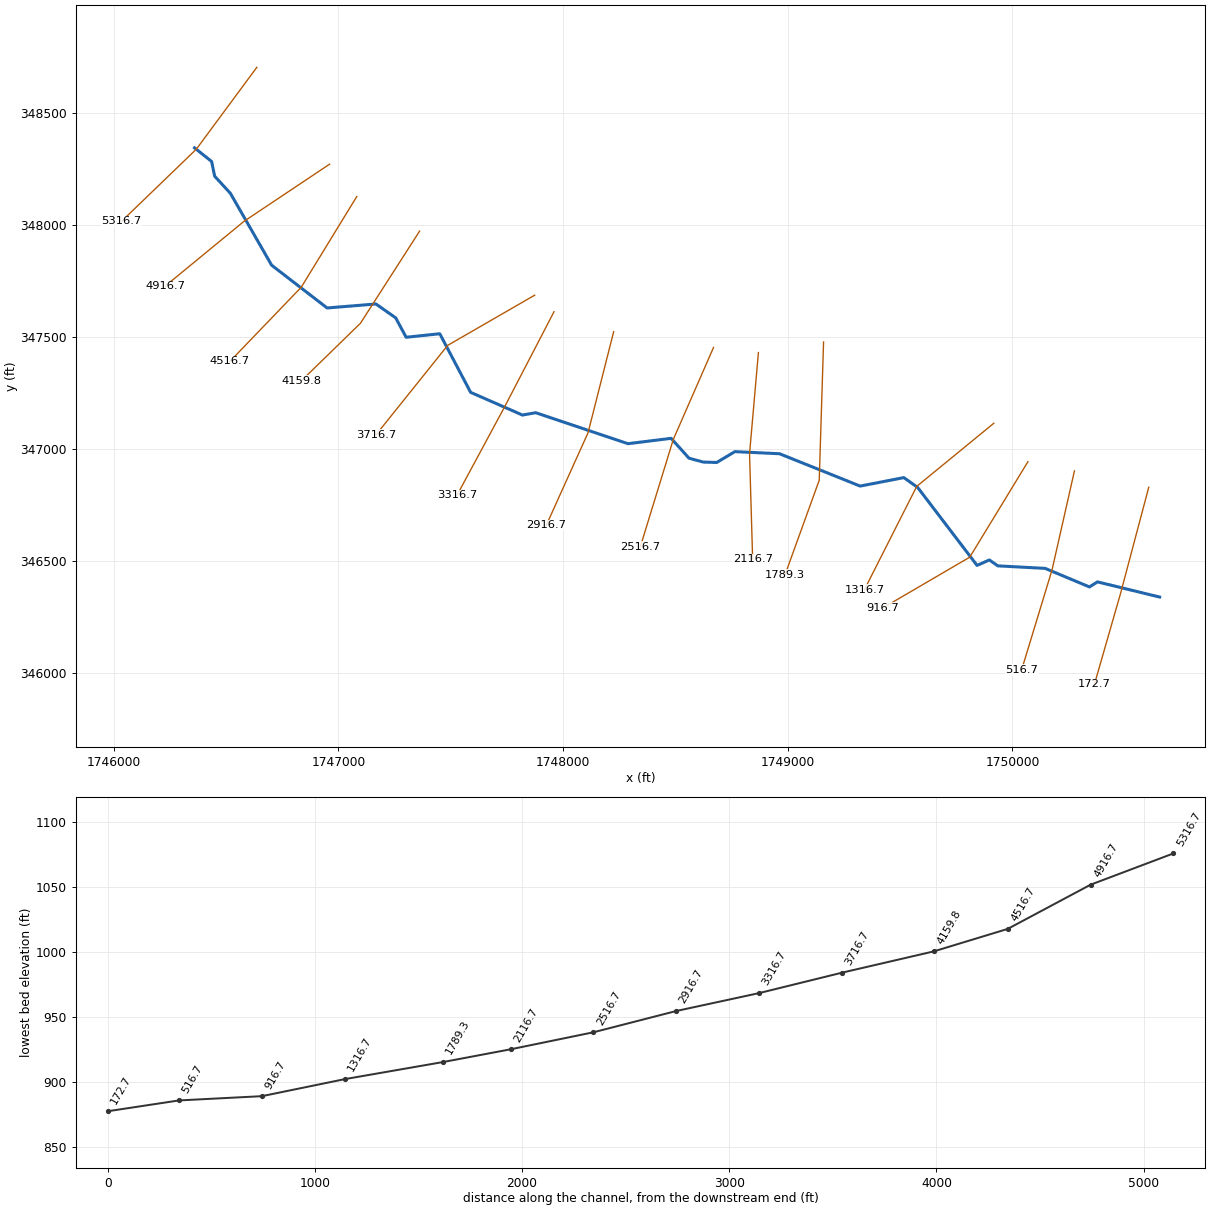
--- CmpRn1.prj (project) ---

Proj Title=CmpRn1
Current Plan=p01
Default Exp/Contr=0,0
English Units
Geom File=g01
Flow File=f01
Plan File=p01
BEGIN DESCRIPTION:
END DESCRIPTION:
DSS Export Rating Curves= 0
DSS Export Rating Curve Sorted= 0
DSS Export Volume Flow Curves= 0
DXF OffsetX= 0
DXF OffsetY= 0
DXF ScaleX= 0
DXF ScaleY= 0

--- CmpRn1.p01 (plan) ---

Plan Title=Floodplain
Program Version=4.00
Geom File=g01
Flow File=f01
K Sum by GR=0
Std Step Tol=0.01
Critical Tol=0.01
Num of Std Step Trials=20
Max Error Tol=0.3
Flow Tol Ratio=0.001
Split Flow NTrial=30
Split Flow Tol=0.02
Split Flow Ratio=0.02
Log Output Level=0
Friction Slope Method=1
Unsteady Friction Slope Method=2
Unsteady Bridges Friction Slope Method=1
Global Log Level=0
CheckData=False
Run HTab=0
Run UNet=0
Run PostProcess=0
UNET Theta=0
UNET Theta Warmup=0
UNET ZTol=0
UNET ZSATol=0
UNET MxIter=0
UNET MaxInSteps=0
UNET DtIC=0
UNET DtMin=0
UNET MaxCRTS=0
UNET WFStab=0
UNET SFStab=0
UNET WFX=0
UNET SFX=0
UNET DSS MLevel=0
UNET DZMax Abort=0
UNET Convert EG Bridges=0
UNET Use Existing IB Tables=0
UNET Froude Limit=0
UNET Froude Power=0
Write IC File=0
Echo Input=False
Echo Output=False
Write Detailed=0

--- CmpRn1.f01 (steady flow) ---

Flow Title=NFF Regression Equation
Program Version=4.00
Number of Profiles=1
Profile Names=P100yr
River Rch & RM=CmpRn1,Main      ,5316.7
622.9331
River Rch & RM=CmpRn1,Main      ,4159.8
660.1297
River Rch & RM=CmpRn1,Main      ,2516.7
726.2800
River Rch & RM=CmpRn1,Main      ,172.7
796.5905
Boundary for River Rch & Prof#=CmpRn1,Main      ,1
Up Type=0
Dn Type=3
Dn Slope=0.024669

--- CmpRn1.g01 (geometry) ---

Geom Title=USGS 3m DEM
Program Version=4.00

River Reach=CmpRn1     ,Main
Reach XY= 30
     1746359.999      348342.722     1746436.011      348281.972
     1746449.684      348216.150     1746519.550      348140.005
     1746703.116      347819.415     1746950.023      347628.638
     1747167.274      347646.464     1747255.163      347584.636
     1747301.747      347498.072     1747451.380      347513.743
     1747588.706      347252.425     1747819.315      347151.193
     1747878.437      347161.548     1748288.807      347023.403
     1748480.978      347047.320     1748560.591      346958.640
     1748623.972      346941.421     1748683.985      346939.741
     1748764.692      346988.074     1748963.295      346978.661
     1749322.116      346834.445     1749516.488      346872.151
     1749578.031      346828.327     1749842.391      346480.573
     1749896.928      346505.021     1749934.540      346478.693
     1750145.165      346467.409     1750342.626      346384.664
     1750378.357      346407.231     1750654.802      346339.530

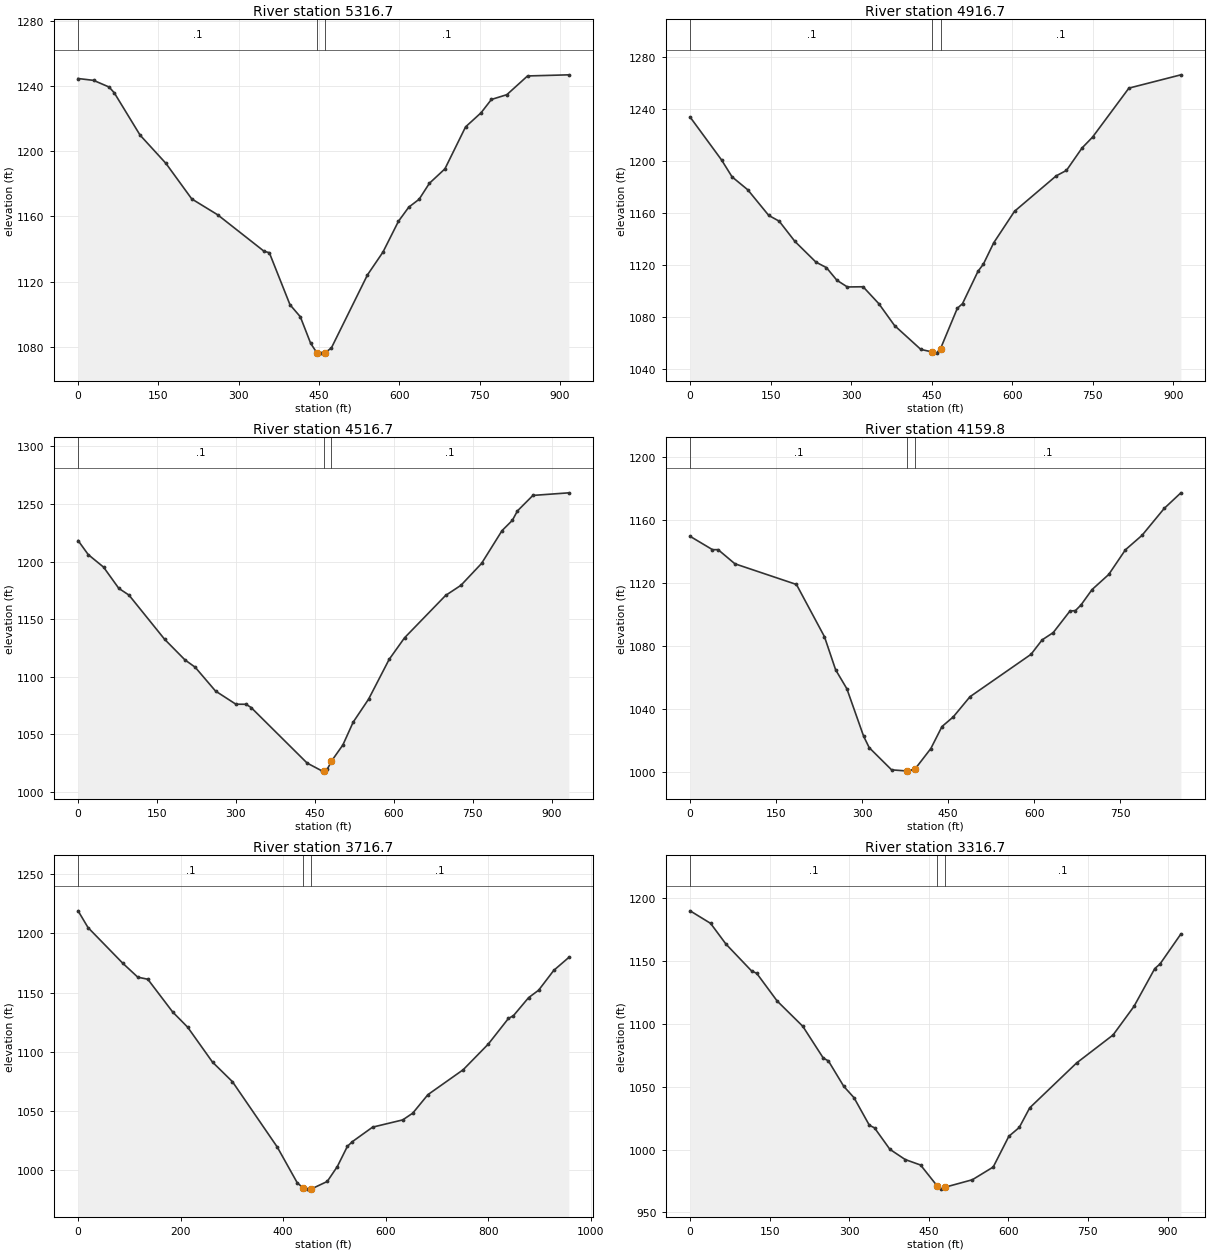
Type RM Length L Ch R = 1 ,5316.7,407.676,400,398.37
XS GIS Cut Line= 3
     1746637.332      348701.840     1746368.046      348336.786
     1746035.364      348015.114
#Sta/Elev= 30
       0 1244.46    29.0 1243.32    57.9 1239.24    67.6 1235.68   115.8 1209.75
   164.1 1192.42   212.3 1170.65   260.6 1160.94   347.5 1138.53   357.1 1137.71
   395.7 1105.81   415.0 1098.43   434.3 1082.15   446.1 1076.26   453.6 1076.14
   461.1 1076.43   472.9 1079.25   540.4 1124.10   569.3 1138.06   598.2 1156.92
   617.5 1165.61   636.8 1170.44   656.1 1180.27   685.0 1189.08   723.6 1214.82
   752.5 1223.46   771.8 1231.61   800.7 1234.56   839.3 1246.03   916.4 1246.72
#Mann= 3 , 0 , 0
       0     0.1       0   446.1   0.045       0   461.1     0.1       0
Bank Sta=   446.1,   461.1
Exp/Cntr=0.3,0.1

Type RM Length L Ch R = 1 ,4916.7,389.918,400,402.539
XS GIS Cut Line= 3
     1746961.293      348270.036     1746579.994      348014.892
     1746228.742      347725.581
#Sta/Elev= 30
       0 1233.75    58.6 1200.71    78.1 1187.73   107.4 1177.75   146.4 1158.03
   165.9 1153.60   195.2 1138.00   234.3 1122.08   253.8 1117.86   273.3 1108.13
   292.8 1102.97   322.1 1103.12   351.4 1090.08   380.7 1073.24   429.5 1054.91
   451.3 1052.87   458.8 1052.03   466.3 1055.52   497.5 1086.53   507.2 1090.13
   536.2 1115.17   545.9 1120.43   565.3 1136.96   604.0 1161.21   681.5 1188.46
   700.8 1192.72   729.9 1210.03   749.3 1218.29   817.0 1256.04   913.8 1266.28
#Mann= 3 , 0 , 0
       0     0.1       0   451.3   0.045       0   466.3     0.1       0
Bank Sta=   451.3,   466.3
Exp/Cntr=0.3,0.1

Type RM Length L Ch R = 1 ,4516.7,358.915,356.938,360.244
XS GIS Cut Line= 3
     1747082.076      348125.640     1746834.958      347721.155
     1746517.299      347390.279
#Sta/Elev= 30
       0 1218.29    19.3 1206.07    48.4 1195.20    77.4 1176.74    96.7 1170.90
   164.4 1132.53   203.1 1114.61   222.5 1108.26   261.2 1087.55   299.9 1076.11
   319.2 1076.05   328.9 1073.22   435.3 1024.98   464.3 1017.97   466.5 1018.42
   474.0 1019.93   481.5 1026.60   503.3 1040.75   522.8 1060.50   552.1 1080.47
   591.1 1114.97   620.4 1133.76   698.5 1170.59   727.7 1179.41   766.8 1198.38
   805.8 1226.93   825.3 1235.81   835.1 1244.05   864.4 1257.48   932.7 1259.73
#Mann= 3 , 0 , 0
       0     0.1       0   466.5   0.045       0   481.5     0.1       0
Bank Sta=   466.5,   481.5
Exp/Cntr=0.3,0.1

Type RM Length L Ch R = 1 ,4159.8,453.029,443.062,442.399
XS GIS Cut Line= 3
     1747361.613      347971.369     1747098.384      347560.475
     1746835.156      347303.667
#Sta/Elev= 30
       0 1149.86    39.0 1141.39    48.8 1141.39    78.1 1132.41   185.4 1119.27
   234.2 1086.11   253.7 1065.05   273.3 1053.00   302.5 1022.85   312.3 1015.55
   351.3 1001.46   377.8 1000.75   380.6 1000.65   392.8 1002.28   419.7 1015.00
   439.2 1029.01   458.7 1035.06   488.0 1047.94   594.4 1074.88   613.8 1084.06
   633.1 1088.68   662.2 1102.35   671.9 1102.69   681.5 1106.22   700.9 1116.06
   729.9 1125.62   759.0 1141.31   788.0 1150.51   826.7 1167.62   855.7 1177.51
#Mann= 3 , 0 , 0
       0     0.1       0   377.8   0.045       0   392.8     0.1       0
Bank Sta=   377.8,   392.8
Exp/Cntr=0.3,0.1

Type RM Length L Ch R = 1 ,3716.7,386.709,400,403.645
XS GIS Cut Line= 3
     1747873.533      347685.555     1747486.712      347462.015
     1747167.832      347063.410
#Sta/Elev= 30
       0 1219.11    19.4 1204.98    87.4 1174.78   116.5 1163.11   136.0 1161.38
   184.5 1133.75   213.7 1120.93   262.2 1091.44   301.1 1074.91   388.5 1019.76
   427.3  989.73   439.3  984.99   446.8  984.25   454.3  984.25   486.0  990.72
   505.7 1003.33   525.3 1020.39   535.1 1024.35   574.4 1036.55   633.3 1042.68
   652.9 1048.43   682.4 1064.00   751.1 1084.99   800.2 1106.71   839.4 1128.29
   849.2 1130.65   878.7 1145.84   898.3 1152.13   927.8 1168.85   957.2 1179.80
#Mann= 3 , 0 , 0
       0     0.1       0   439.3   0.045       0   454.3     0.1       0
Bank Sta=   439.3,   454.3
Exp/Cntr=0.3,0.1

Type RM Length L Ch R = 1 ,3316.7,394.265,400,402.068
XS GIS Cut Line= 3
     1747959.914      347612.166     1747742.232      347192.104
     1747528.195      346793.921
#Sta/Elev= 30
       0 1189.72    38.6 1179.75    67.6 1163.27   115.9 1141.92   125.5 1140.08
   164.1 1118.03   212.4 1097.96   251.0 1072.73   260.7 1070.42   289.7 1050.21
   309.0 1041.17   337.9 1019.28   347.6 1017.23   376.6 1000.17   405.5  992.03
   434.5  987.67   465.6  971.15   473.1  968.52   480.6  970.04   532.1  975.98
   571.4  986.09   600.9 1010.53   620.5 1017.53   640.2 1033.12   728.6 1068.80
   797.4 1091.06   836.7 1113.71   876.0 1143.83   885.9 1147.48   925.2 1171.30
#Mann= 3 , 0 , 0
       0     0.1       0   465.6   0.045       0   480.6     0.1       0
Bank Sta=   465.6,   480.6
Exp/Cntr=0.3,0.1

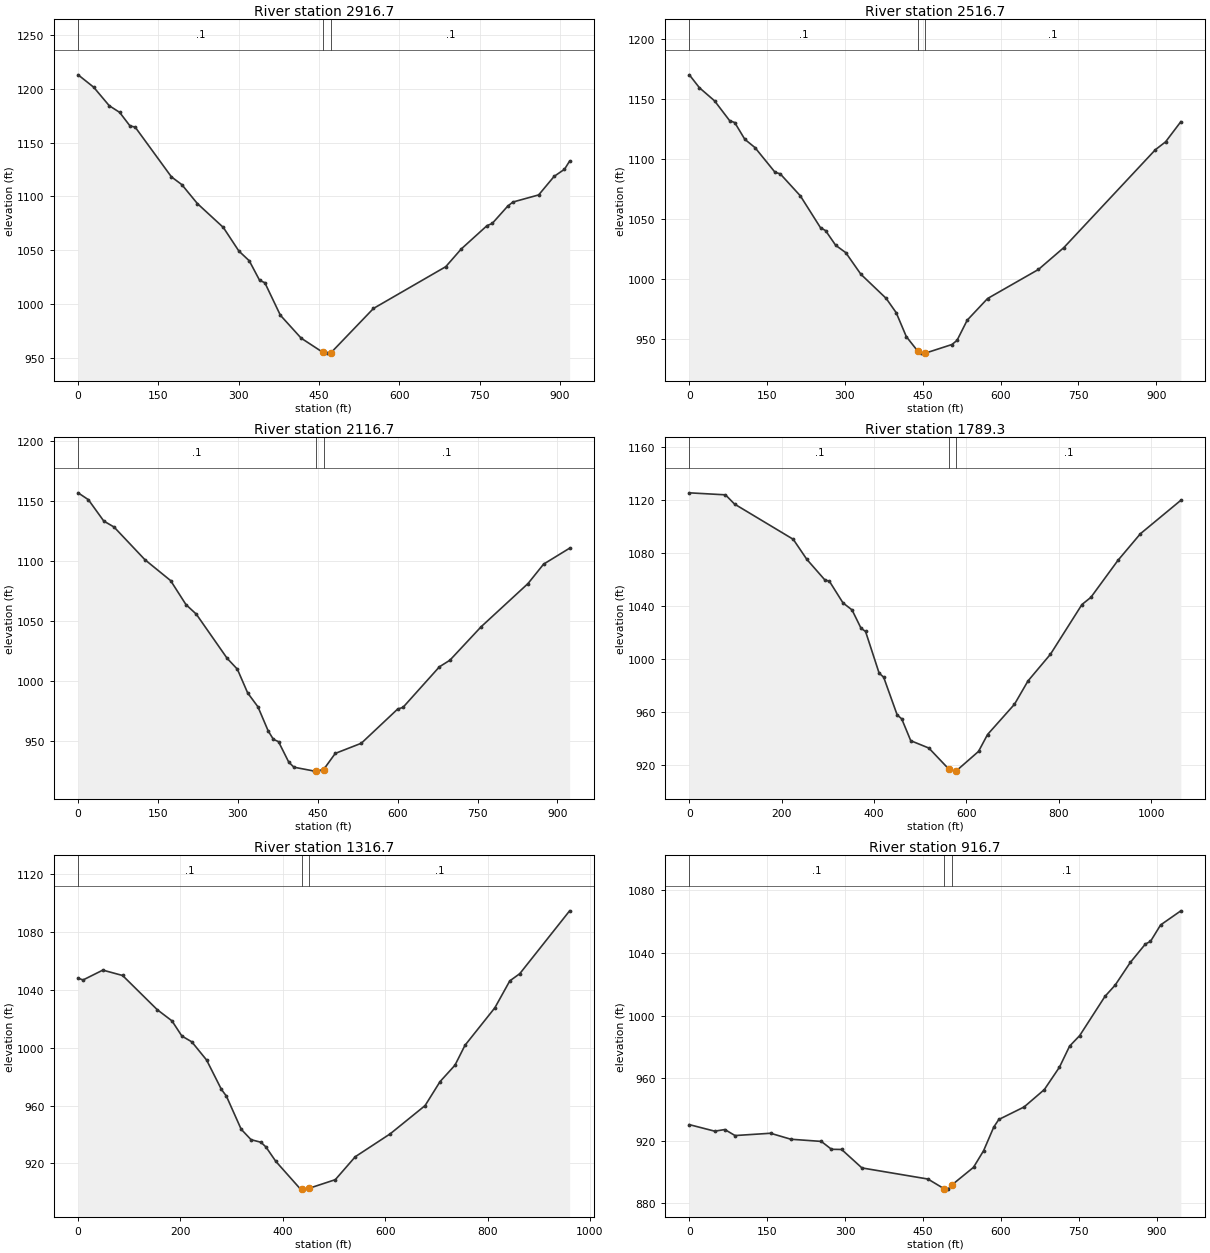
Type RM Length L Ch R = 1 ,2916.7,403.512,400,403.102
XS GIS Cut Line= 3
     1748225.281      347523.122     1748111.286      347072.428
     1747925.195      346659.385
#Sta/Elev= 30
       0 1212.75    29.1 1201.26    58.1 1184.13    77.5 1177.97    96.9 1165.35
   106.5 1164.32   174.3 1118.12   193.7 1110.94   222.8 1093.35   271.2 1071.24
   300.2 1049.38   319.6 1040.35   339.0 1022.17   348.7 1020.01   377.7  989.87
   416.5  968.62   457.4  955.34   464.9  954.72   472.4  955.19   551.6  996.15
   686.6 1034.87   715.5 1051.28   763.7 1072.95   773.3 1074.91   802.2 1090.95
   811.9 1094.79   860.1 1101.41   889.0 1118.61   908.3 1125.18   917.9 1132.78
#Mann= 3 , 0 , 0
       0     0.1       0   457.4   0.045       0   472.4     0.1       0
Bank Sta=   457.4,   472.4
Exp/Cntr=0.3,0.1

Type RM Length L Ch R = 1 ,2516.7,392.302,400,407.758
XS GIS Cut Line= 3
     1748669.614      347452.530     1748490.553      347042.456
     1748343.949      346564.349
#Sta/Elev= 30
       0 1170.45    19.5 1159.66    48.6 1148.77    77.8 1132.17    87.5 1130.64
   107.0 1116.65   126.5 1109.79   165.4 1089.08   175.1 1087.92   214.0 1069.51
   252.9 1042.90   262.6 1040.55   282.1 1028.28   301.6 1022.12   330.7 1004.11
   379.4  984.00   398.8  972.06   418.3  952.09     440  940.20   447.5  938.32
     455  938.32   506.3  945.51   516.1  948.99   535.7  965.82   574.9  983.85
   673.0 1008.10   722.0 1026.35   898.5 1108.02   918.1 1114.55   947.5 1131.37
#Mann= 3 , 0 , 0
       0     0.1       0     440   0.045       0     455     0.1       0
Bank Sta=     440,     455
Exp/Cntr=0.3,0.1

Type RM Length L Ch R = 1 ,2116.7,326.284,327.427,325.905
XS GIS Cut Line= 3
     1748869.355      347429.981     1748829.862      346978.195
     1748843.664      346508.870
#Sta/Elev= 30
       0 1157.08    19.3 1151.35    48.2 1133.56    67.5 1128.58   125.4 1101.37
   173.7 1083.95   202.6 1063.91   221.9 1056.02   279.8 1019.22   299.1 1010.11
   318.4  990.36   337.7  978.78   357.0  958.64   366.7  951.69   376.3  949.76
   395.6  932.66   405.3  928.48   443.9  925.20     446  925.20     461  926.53
   482.9  939.96   531.8  948.43   600.2  976.97   610.0  978.27   678.5 1012.14
   698.1 1017.59   756.7 1045.44   844.8 1081.47   874.1 1097.66   923.0 1110.96
#Mann= 3 , 0 , 0
       0     0.1       0     446   0.045       0     461     0.1       0
Bank Sta=     446,     461
Exp/Cntr=0.3,0.1

Type RM Length L Ch R = 1 ,1789.3,491.845,472.573,463.195
XS GIS Cut Line= 3
     1749159.271      347477.013     1749140.011      346860.673
     1748987.972      346439.284
#Sta/Elev= 30
       0 1125.44    78.3 1123.92    97.9 1116.96   225.1 1090.35   254.5 1075.22
   293.6 1059.67   303.4 1058.69   332.8 1042.36   352.4 1037.05   371.9 1023.22
   381.7 1020.78   411.1  989.32   420.9  986.27   450.2  957.75   460.0  954.82
   479.6  938.32   518.8  932.77   562.8  916.62   577.5  915.35   577.8  915.43
   626.4  930.23   645.9  942.97   704.3  965.84   733.5  983.42   782.2 1003.60
   850.4 1041.12   869.8 1046.56   928.3 1074.43   977.0 1094.55  1064.6 1119.81
#Mann= 3 , 0 , 0
       0     0.1       0   562.8   0.045       0   577.8     0.1       0
Bank Sta=   562.8,   577.8
Exp/Cntr=0.3,0.1

Type RM Length L Ch R = 1 ,1316.7,391.284,400,386.175
XS GIS Cut Line= 3
     1749917.157      347114.780     1749573.854      346833.038
     1749341.054      346372.320
#Sta/Elev= 30
       0 1048.02     9.7 1046.79    48.3 1053.59    86.9 1049.87   154.5 1026.27
   183.4 1018.50   202.7 1008.04   222.1 1004.02   251.0  991.46   280.0  971.13
   289.6  966.57   318.6  943.61   337.9  936.40   357.2  934.62   366.9  931.39
   386.2  921.45   434.5  902.23   436.6  902.23   451.6  902.84   502.5  908.77
   541.5  924.62   609.7  940.43   677.9  959.96   707.1  976.52   736.3  987.88
   755.8 1001.60   814.2 1027.54   843.4 1046.15   862.9 1051.12   960.3 1094.56
#Mann= 3 , 0 , 0
       0     0.1       0   436.6   0.045       0   451.6     0.1       0
Bank Sta=   436.6,   451.6
Exp/Cntr=0.3,0.1

Type RM Length L Ch R = 1 ,916.7,389.335,400,419.07
XS GIS Cut Line= 3
     1750068.904      346943.503     1749809.858      346517.430
     1749423.296      346291.131
#Sta/Elev= 30
       0  930.32    48.9  926.14    68.4  927.18    88.0  923.34   156.4  924.81
   195.5  920.99   254.2  919.60   273.8  914.56   293.3  914.45   332.4  902.66
   459.5  895.56   491.1  889.27   498.6  889.11   506.1  891.90   547.3  903.04
   566.8  913.71   586.3  928.76   596.0  933.60   644.7  941.60   683.7  952.71
   712.9  967.07   732.3  980.46   751.8  987.21   800.5 1012.27   820.0 1019.41
   849.2 1033.92   878.4 1045.75   888.1 1047.37   907.6 1057.90   946.6 1066.93
#Mann= 3 , 0 , 0
       0     0.1       0   491.1   0.045       0   506.1     0.1       0
Bank Sta=   491.1,   506.1
Exp/Cntr=0.3,0.1

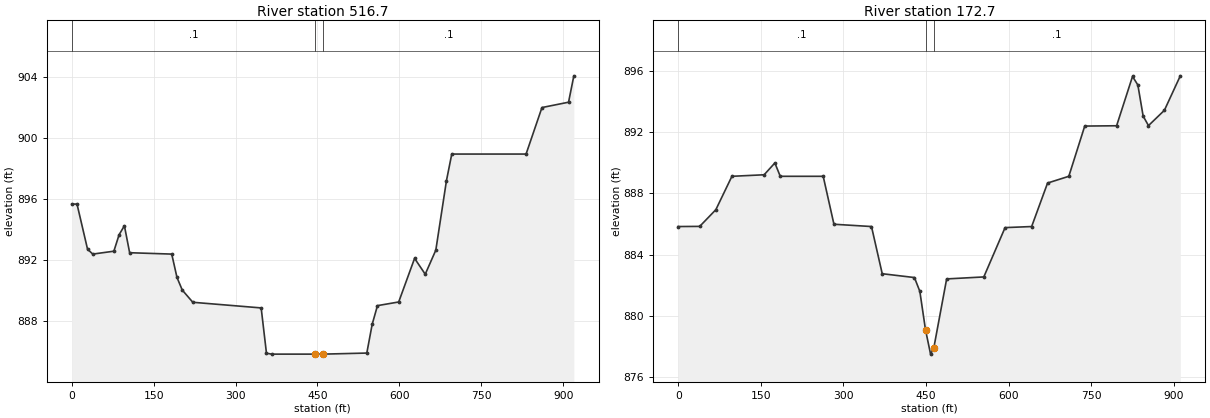
Type RM Length L Ch R = 1 ,516.7,342.067,344.055,345.476
XS GIS Cut Line= 3
     1750275.727      346902.280     1750175.962      346460.455
     1750040.353      346013.972
#Sta/Elev= 30
       0  895.67     9.6  895.67    28.9  892.71    38.5  892.39    77.1  892.58
    86.7  893.66    96.4  894.25   106.0  892.48   183.1  892.39   192.7  890.86
   202.4  890.03   221.7  889.23   346.9  888.86   356.6  885.89   366.2  885.83
   445.4  885.83   460.4  885.83   540.4  885.90   550.2  887.78   559.9  889.01
   598.8  889.25   627.9  892.11   647.4  891.07   666.8  892.65   686.3  897.21
   696.0  898.95   832.1  898.95   861.2  902.00   909.9  902.35   919.6  904.08
#Mann= 3 , 0 , 0
       0     0.1       0   445.4   0.045       0   460.4     0.1       0
Bank Sta=   445.4,   460.4
Exp/Cntr=0.3,0.1

Type RM Length L Ch R = 1 ,172.7,173.707,172.663,171.62
XS GIS Cut Line= 3
     1750606.467      346829.277     1750481.541      346358.040
     1750364.523      345950.055
#Sta/Elev= 30
       0  885.83    39.0  885.84    68.3  886.93    97.5  889.11   156.0  889.21
   175.5  889.98   185.3  889.11   263.3  889.11   282.8  885.98   351.0  885.83
   370.5  882.75   429.0  882.50   438.8  881.60   449.1  879.09   458.3  877.50
   464.1  877.89   487.5  882.41   555.0  882.54   593.6  885.76   641.9  885.83
   670.8  888.67   709.4  889.11   738.3  892.39   796.2  892.41   825.1  895.63
   834.8  895.07   844.4  893.04   854.1  892.42   883.0  893.42   911.9  895.67
#Mann= 3 , 0 , 0
       0     0.1       0   449.1   0.045       0   464.1     0.1       0
Bank Sta=   449.1,   464.1
Exp/Cntr=0.3,0.1